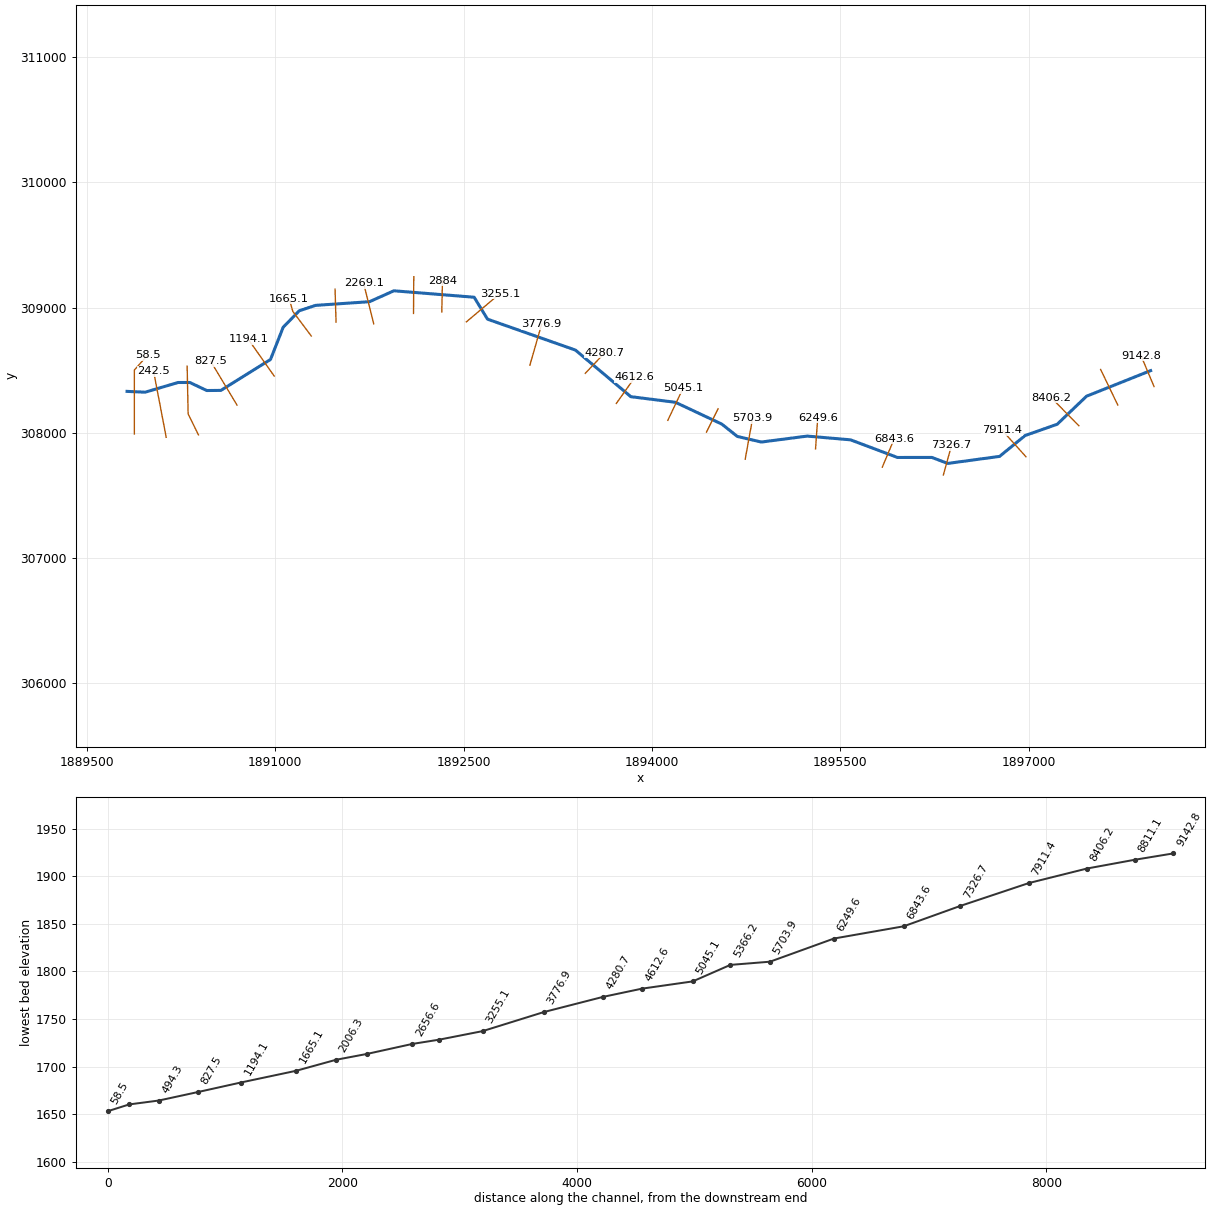
--- FROGCK.prj (project) ---

Proj Title=FROGCK
Current Plan=p01
Geom File=g01
Flow File=f01
Plan File=p01
DSS Export Rating Curves=0
DSS Export Rating Curve Sorted=0
DSS Export Volume Flow Curves=0
DXF OffsetX=0
DXF OffsetY=0
DXF ScaleX=0
DXF ScaleY=0

--- FROGCK.p01 (plan) ---

Plan Title=Floodplain
Program Version=4.00
Geom File=g01
Flow File=f01
K Sum by GR=0
Std Step Tol=0.01
Critical Tol=0.01
Num of Std Step Trials=20
Max Error Tol=0.3
Flow Tol Ratio=0.001
Split Flow NTrial=30
Split Flow Tol=0.02
Split Flow Ratio=0.02
Log Output Level=0
Friction Slope Method=1
Unsteady Friction Slope Method=2
Unsteady Bridges Friction Slope Method=1
Global Log Level=0
CheckData=False
Run HTab=0
Run UNet=0
Run PostProcess=0
UNET Theta=0
UNET Theta Warmup=0
UNET ZTol=0
UNET ZSATol=0
UNET MxIter=0
UNET MaxInSteps=0
UNET DtIC=0
UNET DtMin=0
UNET MaxCRTS=0
UNET WFStab=0
UNET SFStab=0
UNET WFX=0
UNET SFX=0
UNET DSS MLevel=0
UNET DZMax Abort=0
UNET Convert EG Bridges=0
UNET Use Existing IB Tables=0
UNET Froude Limit=0
UNET Froude Power=0
Write IC File=0
Echo Input=False
Echo Output=False
Write Detailed=0

--- FROGCK.f01 (steady flow) ---

Flow Title=NFF Regression Equation
Program Version=4.10
Number of Profiles= 1
Profile Names=P100yr
River Rch & RM=FROGCK,Main            ,9142.8
551.2881
River Rch & RM=FROGCK,Main            ,7326.7
613.7267
River Rch & RM=FROGCK,Main            ,5703.9
673.6052
River Rch & RM=FROGCK,Main            ,5045.1
845.2606
River Rch & RM=FROGCK,Main            ,242.5
 938.361
Boundary for River Rch & Prof#=FROGCK,Main            , 1
Up Type= 0
Dn Type= 1
Dn Known WS=1656.19
DSS Import GetInterval= 0
DSS Import GetPeak= 0
DSS Import FillOption= 0

--- FROGCK.g01 (geometry) ---

Geom Title=USGS 10m DEM
Program Version=4.10

River Reach=FROGCK          ,Main
Reach XY= 30
     1897970.644      308496.598     1897460.176      308292.375
     1897226.349       308068.61      1896971.25      307978.655
     1896767.434       307811.99     1896354.706      307756.032
     1896229.069      307803.775     1895954.579      307803.611
     1895581.315      307944.236     1895236.358      307974.131
     1894870.503      307926.634     1894679.232      307971.564
     1894556.442      308069.703      1894186.71      308243.902
     1893831.572      308288.737     1893390.395      308660.655
     1892690.777      308907.126      1892584.23      309082.223
     1891944.946      309133.571     1891751.454      309046.666
     1891320.898      309017.152      1891192.08      308974.352
     1891063.608      308842.408     1890962.913      308585.463
     1890567.673      308338.767     1890455.665      308337.749
     1890320.236        308401.9     1890227.575        308401.9
     1889964.864      308324.512     1889820.407      308330.914

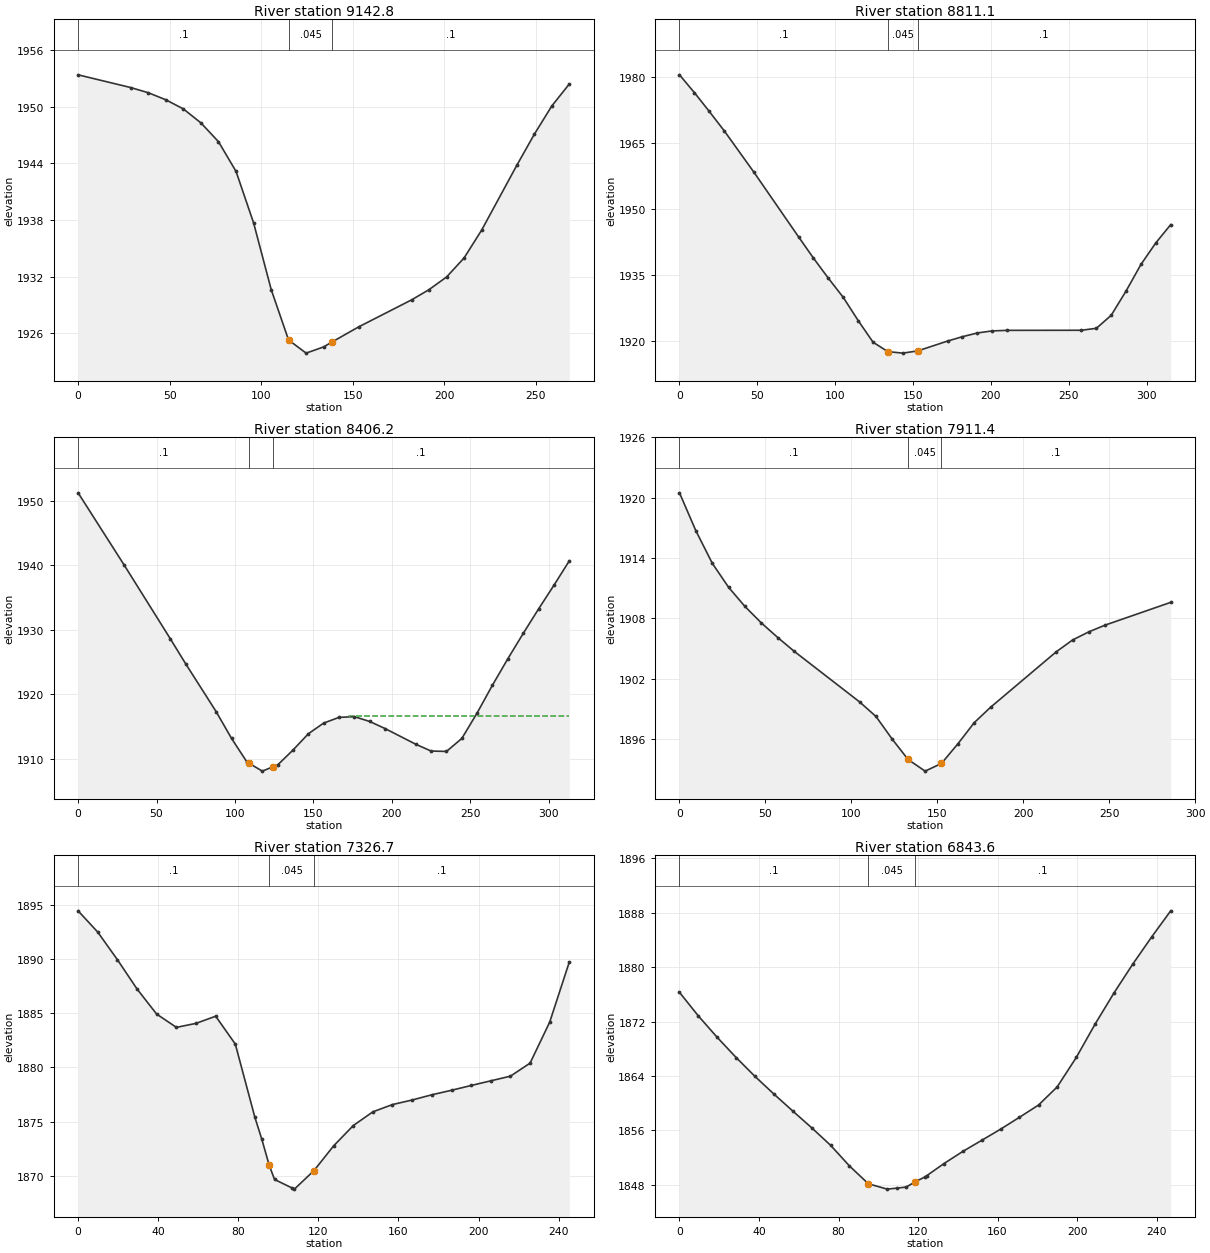
Type RM Length L Ch R = 1 ,9142.8  ,330.6,331.7,332.8
XS GIS Cut Line= 2
     1897997.732      308369.096     1897893.566      308616.492
#Sta/Elev= 24
       0 1953.39    28.8 1952.04    38.4 1951.49    47.9 1950.75    57.5 1949.78
    67.1  1948.3    76.7 1946.31    86.3 1943.16    95.9  1937.7   105.5 1930.65
     115  1925.3   124.6 1923.91   134.2 1924.57     139 1925.12   153.4  1926.7
   182.2 1929.55   191.7 1930.63   201.3 1931.97   210.9 1933.99   220.5 1936.94
   239.7  1943.8   249.3  1947.1   258.8 1950.08   268.4 1952.42
#Mann= 3 , 0 , 0
       0      .1       0     115    .045       0     139      .1       0
Bank Sta=115,139
XS Rating Curve= 0 ,0
Exp/Cntr=0.3,0.1

Type RM Length L Ch R = 1 ,8811.1  ,397.5,404.9,412.3
XS GIS Cut Line= 2
     1897709.104      308221.527     1897572.385      308505.815
#Sta/Elev= 26
       0 1980.49     9.6 1976.43    19.1 1972.18    28.7 1967.77    47.8 1958.34
    76.5 1943.62      86 1938.82    95.6 1934.23   105.2 1929.86   114.7 1924.62
   124.3 1919.68   133.8 1917.54   143.4  1917.2     153 1917.71   172.1 1919.94
   181.6 1920.93   191.2 1921.78   200.7 1922.25   210.3 1922.38   258.1  1922.4
   267.7 1922.85   277.2  1925.8   286.8 1931.36   296.3 1937.37   305.9  1942.3
   315.4 1946.42
#Mann= 3 , 0 , 0
       0      .1       0   133.8    .045       0     153      .1       0
Bank Sta=133.8,153
XS Rating Curve= 0 ,0
Exp/Cntr=0.3,0.1

Type RM Length L Ch R = 1 ,8406.2  ,495.7,494.8,493.7
XS GIS Cut Line= 2
     1897398.774      308056.596      1897179.59      308280.121
#Sta/Elev= 29
       0 1951.27    29.4 1940.04    58.7 1928.63    68.5 1924.74      88 1917.28
    97.8 1913.12   107.6 1909.46     109 1909.26   117.4 1908.04     124 1908.69
   127.2    1909     137 1911.32   146.8 1913.85   156.5  1915.5   166.3 1916.39
   176.1  1916.5   185.9 1915.75   195.7 1914.65   215.2 1912.22     225 1911.16
   234.8  1911.1   244.6 1913.12   254.4  1917.1   264.1 1921.39   273.9 1925.49
   283.7 1929.42   293.5 1933.23   303.3 1936.91   313.1 1940.71
#Mann= 3 , 0 , 0
       0      .1       0     109    .045       0     124      .1       0
#XS Ineff= 2 , 0
                          172.54         1916.53
Permanent Ineff=
       F       F
Bank Sta=109,124
XS Rating Curve= 0 ,0
Exp/Cntr=0.3,0.1

Type RM Length L Ch R = 1 ,7911.4  ,607.8,584.7,561.7
XS GIS Cut Line= 2
     1896977.767        307809.2     1896786.795      308021.874
#Sta/Elev= 22
       0 1920.49     9.5 1916.73    19.1 1913.48    28.6 1911.09    38.1 1909.19
    47.6 1907.56    57.2  1906.1    66.7 1904.74   104.8  1899.7   114.3 1898.26
   123.9 1895.97     133 1893.98   142.9 1892.82   152.4 1893.58     162 1895.54
   171.5 1897.64     181 1899.17   219.1 1904.67   228.7 1905.86   238.2 1906.67
   247.7 1907.34   285.8  1909.6
#Mann= 3 , 0 , 0
       0      .1       0     133    .045       0   152.4      .1       0
Bank Sta=133,152.4
XS Rating Curve= 0 ,0
Exp/Cntr=0.3,0.1

Type RM Length L Ch R = 1 ,7326.7  ,485.8,483.2,479.9
XS GIS Cut Line= 2
     1896320.215      307663.801     1896385.319      307900.346
#Sta/Elev= 29
       0 1894.45     9.8 1892.49    19.6 1889.95    29.4 1887.25    39.2 1884.93
    49.1  1883.7    58.9 1884.07    68.7 1884.73    78.5 1882.16    88.3 1875.39
    91.7 1873.41   95.42 1870.99    98.1 1869.67   106.7  1868.9     108 1868.78
   117.8 1870.49   127.6 1872.77   137.4 1874.64   147.2 1875.91     157 1876.58
   166.8    1877   176.6 1877.48   186.5  1877.9   196.3 1878.34   206.1 1878.77
   215.9  1879.2   225.7  1880.4   235.5 1884.18   245.3 1889.73
#Mann= 3 , 0 , 0
       0      .1       0   95.42    .045       0   117.8      .1       0
Bank Sta=95.42,117.8
XS Rating Curve= 0 ,0
Exp/Cntr=0.3,0.1

Type RM Length L Ch R = 1 ,6843.6  ,586.6,594,601.4
XS GIS Cut Line= 2
     1895834.104      307726.735      1895929.59        307954.6
#Sta/Elev= 30
       0 1876.31     9.5 1872.83      19 1869.68    28.5 1866.72      38 1863.94
    47.5 1861.35      57 1858.85    66.5 1856.39      76 1853.82    85.5 1850.78
      95 1848.16   104.5 1847.37   109.4 1847.52     114 1847.67  118.31  1848.4
   123.5 1849.17   124.4 1849.35     133 1851.12   142.5 1852.91     152 1854.54
   161.5 1856.18     171 1857.93   180.6 1859.73     190  1862.4   199.6 1866.73
     209  1871.6   218.6 1876.23   228.1 1880.49   237.6 1884.48   247.1 1888.29
#Mann= 3 , 0 , 0
       0      .1       0      95    .045       0  118.31      .1       0
Bank Sta=95,118.31
XS Rating Curve= 0 ,0
Exp/Cntr=0.3,0.1

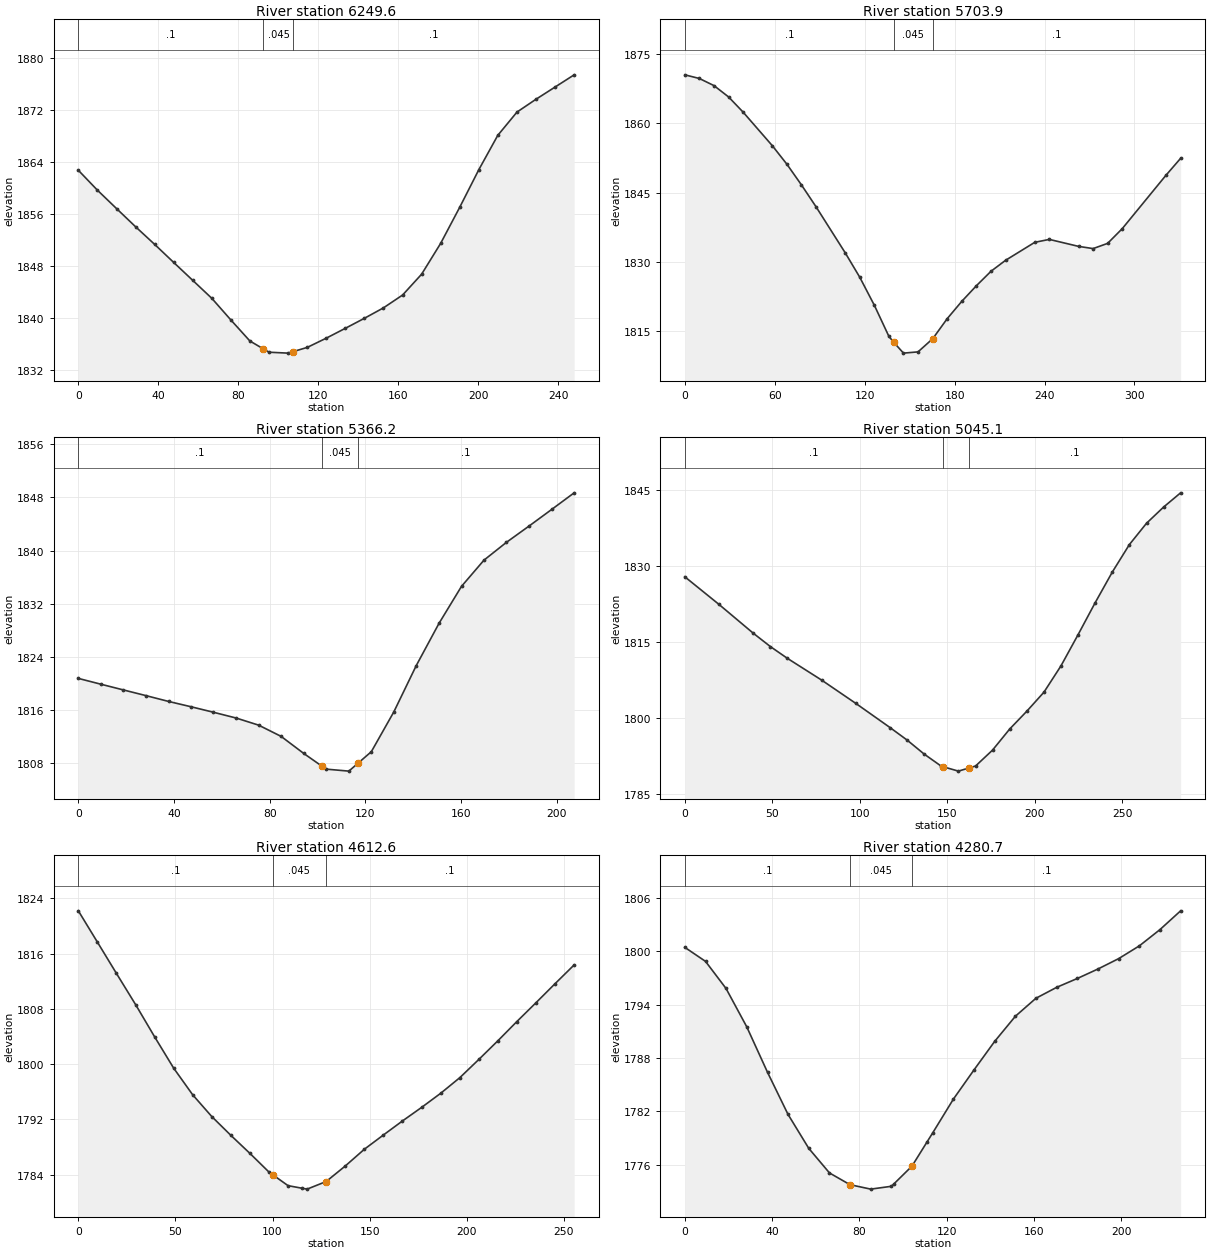
Type RM Length L Ch R = 1 ,6249.6  ,548.1,545.6,543.1
XS GIS Cut Line= 2
      1895302.42      307872.134     1895319.781       308119.53
#Sta/Elev= 29
       0 1862.66     9.5 1859.61    19.1 1856.77    28.6 1853.98    38.2 1851.25
    47.7 1848.48    57.2 1845.73    66.8 1842.95    76.3 1839.63    85.8  1836.4
    92.6 1835.17    95.4 1834.67   104.9 1834.53   107.6 1834.78   114.5 1835.41
     124 1836.83   133.5 1838.34   143.1 1839.89   152.6 1841.49   162.2 1843.47
   171.7 1846.67   181.2  1851.4   190.8 1856.99   200.3 1862.74   209.8 1868.03
   219.4 1871.61   228.9 1873.58   238.5 1875.47     248 1877.34
#Mann= 3 , 0 , 0
       0      .1       0    92.6    .045       0   107.6      .1       0
Bank Sta=92.6,107.6
XS Rating Curve= 0 ,0
Exp/Cntr=0.3,0.1

Type RM Length L Ch R = 1 ,5703.9  ,344.1,337.7,331.3
XS GIS Cut Line= 2
     1894742.524      307789.669     1894801.118       308115.19
#Sta/Elev= 30
       0  1870.5     9.7 1869.71    19.5 1868.16    29.2 1865.71    38.9 1862.42
    58.4 1855.14    68.1 1851.14    77.8 1846.66    87.6 1841.89     107 1831.95
   116.7 1826.66   126.5 1820.54   136.2 1813.81  139.51 1812.51   145.9  1810.2
   155.6 1810.47   165.4 1813.32   175.1 1817.68   184.8 1821.42   194.6 1824.82
   204.3 1827.94     214 1830.31   233.5 1834.21   243.2 1834.84   262.7 1833.33
   272.4 1832.85   282.1 1833.98   291.8 1837.15     321 1848.73   330.8 1852.41
#Mann= 3 , 0 , 0
       0      .1       0  139.51    .045       0   165.4      .1       0
Bank Sta=139.51,165.4
XS Rating Curve= 0 ,0
Exp/Cntr=0.3,0.1

Type RM Length L Ch R = 1 ,5366.2  ,320.8,321.1,321.5
XS GIS Cut Line= 2
     1894434.317      308006.287     1894526.331      308192.051
#Sta/Elev= 25
       0 1820.78     9.4 1819.91    18.8 1819.05    28.3 1818.19    37.7 1817.32
    47.1 1816.52    56.5 1815.69      66 1814.82    75.4 1813.75    84.8 1812.06
    94.2 1809.51   101.9 1807.57   103.6 1807.14   113.1 1806.84   116.9 1808.02
   122.5 1809.76   131.9 1815.74   141.3 1822.72   150.8 1829.06   160.2 1834.62
   169.6 1838.56     179 1841.24   188.5  1843.7   197.9 1846.18   207.3 1848.68
#Mann= 3 , 0 , 0
       0      .1       0   101.9    .045       0   116.9      .1       0
Bank Sta=101.9,116.9
XS Rating Curve= 0 ,0
Exp/Cntr=0.3,0.1

Type RM Length L Ch R = 1 ,5045.1  ,436.4,432.5,428.3
XS GIS Cut Line= 2
     1894126.204      308099.999     1894247.732      308356.075
#Sta/Elev= 27
       0 1827.87    19.6  1822.4    39.1 1816.74    48.9  1814.1    58.6 1811.78
    78.2 1807.48    97.7 1802.89   117.3 1798.11   127.1 1795.63   136.8 1792.88
   146.6 1790.48   147.4  1790.4   156.4 1789.51   162.4 1790.13   166.2 1790.52
   175.9 1793.66   185.7 1797.82   195.5 1801.34   205.3  1805.1     215 1810.28
   224.8 1816.45   234.6 1822.78   244.4 1828.83   254.1 1834.22   263.9 1838.43
   273.7 1841.64   283.4 1844.44
#Mann= 3 , 0 , 0
       0      .1       0   147.4    .045       0   162.4      .1       0
Bank Sta=147.4,162.4
XS Rating Curve= 0 ,0
Exp/Cntr=0.3,0.1

Type RM Length L Ch R = 1 ,4612.6  ,335.2,332,328.7
XS GIS Cut Line= 2
     1893716.048      308234.548     1893863.618      308442.881
#Sta/Elev= 29
       0 1822.19     9.8 1817.67    19.6 1813.14    29.5 1808.61    39.3 1803.94
    49.1 1799.41    58.9 1795.55    68.7 1792.41    78.6 1789.67    88.4 1787.06
    98.2 1784.36     100    1784     108  1782.4     115 1782.04   117.8  1781.9
   127.6    1783   137.5 1785.26   147.3 1787.68   157.1 1789.74   166.9 1791.77
   176.8 1793.74   186.6 1795.78   196.4 1798.03   206.2 1800.67     216 1803.37
   225.8 1806.16   235.7  1808.9   245.5 1811.65   255.3 1814.36
#Mann= 3 , 0 , 0
       0      .1       0     100    .045       0   127.6      .1       0
Bank Sta=100,127.6
XS Rating Curve= 0 ,0
Exp/Cntr=0.3,0.1

Type RM Length L Ch R = 1 ,4280.7  ,492.9,503.8,514.6
XS GIS Cut Line= 2
      1893469.04      308475.037      1893625.29      308639.967
#Sta/Elev= 27
       0 1800.46     9.5 1798.88    18.9 1795.83    28.4 1791.51    37.9  1786.4
    47.3 1781.66    56.8 1777.84    66.3 1775.07    75.7 1773.75    85.2 1773.25
    94.7 1773.57    95.9 1773.86   104.1 1775.84   110.9 1778.52   113.6 1779.58
   123.1 1783.39   132.5 1786.66     142 1789.88   151.5 1792.71   160.9 1794.73
   170.4 1795.96   179.9 1796.96   189.3 1798.02   198.8 1799.19   208.3 1800.63
   217.7 1802.45   227.2 1804.57
#Mann= 3 , 0 , 0
       0      .1       0    75.7    .045       0   104.1      .1       0
Bank Sta=75.7,104.1
XS Rating Curve= 0 ,0
Exp/Cntr=0.3,0.1

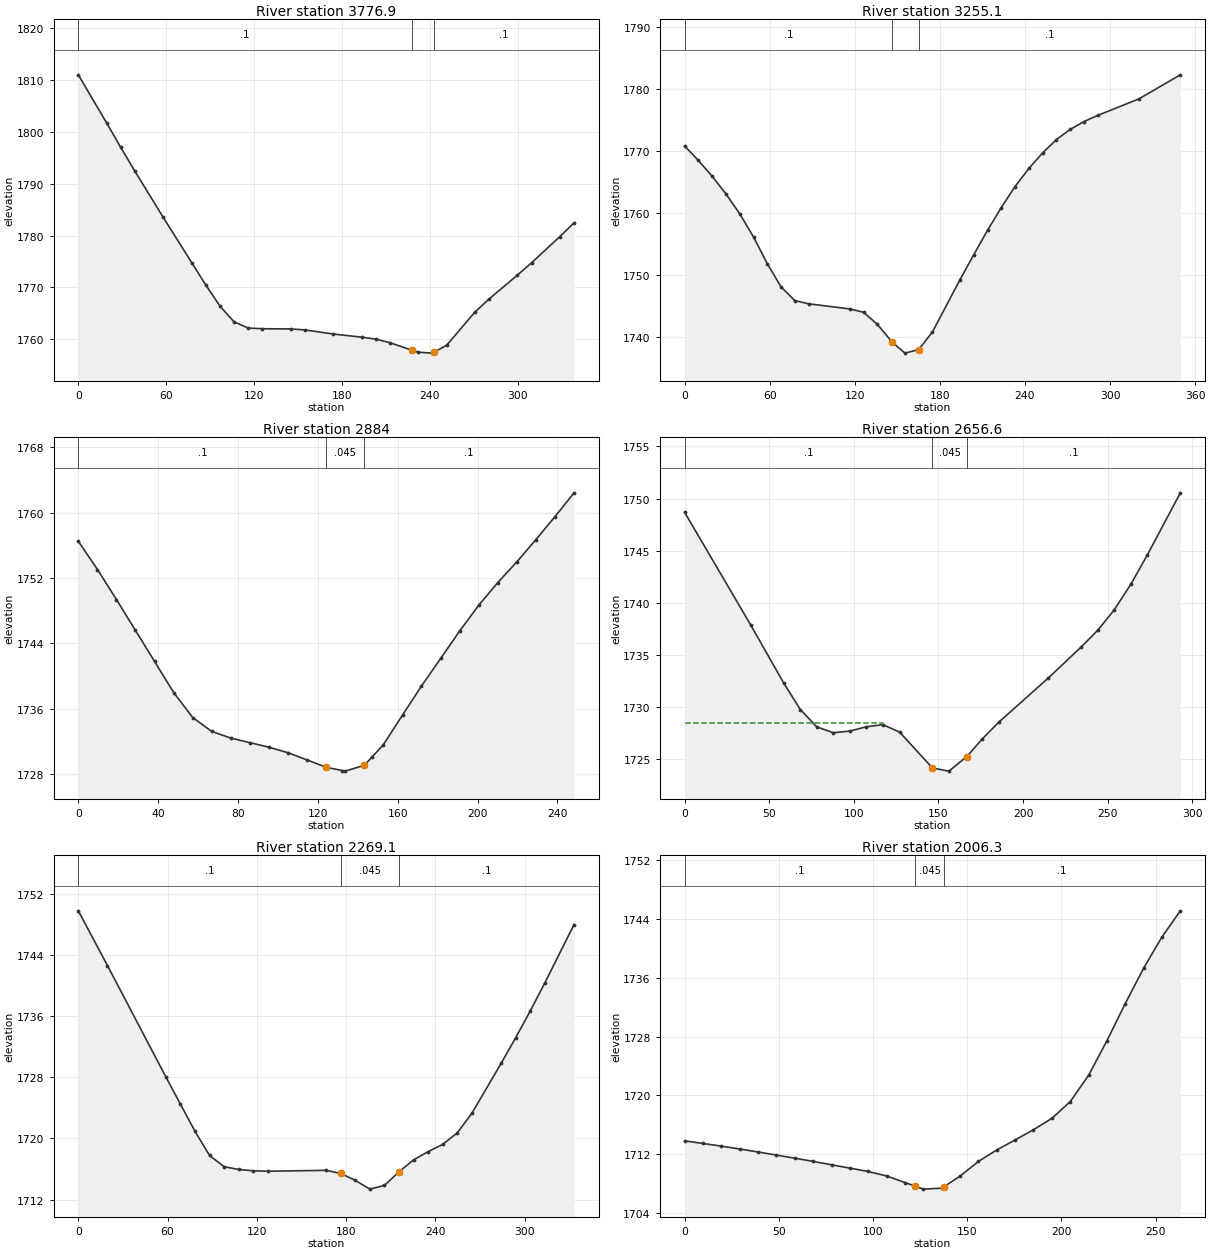
Type RM Length L Ch R = 1 ,3776.9  ,535.1,521.8,508.7
XS GIS Cut Line= 2
     1893028.114      308540.537      1893121.43      308866.058
#Sta/Elev= 28
       0 1810.96    19.4 1801.66      29 1796.96    38.7 1792.36      58  1783.5
    77.4 1774.79    87.1 1770.46    96.8 1766.38   106.4 1763.36   116.1 1762.17
   125.8 1762.04   145.1    1762   154.8 1761.81   174.2 1761.02   193.5 1760.42
   203.2 1760.04   212.8 1759.35   227.9  1757.9   232.2 1757.51   241.9 1757.34
   242.9  1757.5   251.6 1758.86   270.9 1765.25   280.6 1767.78   299.9 1772.36
   309.6 1774.75     329 1779.81   338.6 1782.44
#Mann= 3 , 0 , 0
       0      .1       0   227.9    .045       0   242.9      .1       0
Bank Sta=227.9,242.9
XS Rating Curve= 0 ,0
Exp/Cntr=0.3,0.1

Type RM Length L Ch R = 1 ,3255.1  ,351.6,371.1,390.2
XS GIS Cut Line= 2
     1892522.472      308885.589     1892789.399      309111.284
#Sta/Elev= 30
       0 1770.74     9.7 1768.41    19.4 1765.86    29.1 1763.02    38.8 1759.83
    48.6 1756.05    58.3 1751.75      68 1748.01    77.7  1745.8    87.4 1745.28
   116.5 1744.45   126.2 1743.91   135.9 1741.97   146.2 1739.13   155.4 1737.32
   165.1  1737.9   174.8 1740.75   194.2 1749.18   203.9  1753.2   213.6 1757.13
   223.3 1760.81     233  1764.2   242.8 1767.13   252.5 1769.64   262.2 1771.78
   271.9 1773.42   281.6 1774.68   291.3 1775.68   320.4 1778.35   349.6 1782.23
#Mann= 3 , 0 , 0
       0      .1       0   146.2    .045       0   165.1      .1       0
Bank Sta=146.2,165.1
XS Rating Curve= 0 ,0
Exp/Cntr=0.3,0.1

Type RM Length L Ch R = 1 ,2884    ,227.2,227.4,227.7
XS GIS Cut Line= 2
     1892326.678       308964.62     1892331.887      309212.884
#Sta/Elev= 29
       0 1756.51     9.6 1753.04    19.1 1749.36    28.6 1745.58    38.2 1741.77
    47.8 1737.95    57.3  1734.9    66.8  1733.2    76.4 1732.38      86 1731.82
    95.5 1731.26   105.1 1730.58   114.6  1729.7   124.2  1728.8   132.2  1728.4
   133.7 1728.33   143.3 1729.05   147.2 1730.08   152.8 1731.57   162.4  1735.2
   171.9 1738.77   181.5 1742.14     191  1745.5   200.6 1748.67   210.1 1751.44
   219.7 1753.99   229.2 1756.71   238.8 1759.53   248.3 1762.44
#Mann= 3 , 0 , 0
       0      .1       0   124.2    .045       0   143.3      .1       0
Bank Sta=124.2,143.3
XS Rating Curve= 0 ,0
Exp/Cntr=0.3,0.1

Type RM Length L Ch R = 1 ,2656.6  ,381.9,387.5,393.1
XS GIS Cut Line= 2
     1892101.465      308952.864     1892103.635      309245.832
#Sta/Elev= 22
       0 1748.68    39.1 1737.87    58.6 1732.31    68.4 1729.78    78.1 1728.12
    87.9 1727.56    97.7 1727.72   107.4 1728.13   117.2 1728.33     127 1727.63
   146.5 1724.18   156.2 1723.88   166.8 1725.28   175.8 1726.94   185.6 1728.56
   214.8 1732.78   234.4 1735.78   244.2 1737.38   253.9 1739.33   263.7 1741.78
   273.4 1744.57     293 1750.55
#Mann= 3 , 0 , 0
       0      .1       0   146.5    .045       0   166.8      .1       0
#XS Ineff= 2 , 0
          117.46 1728.48
Permanent Ineff=
       F       F
Bank Sta=146.5,166.8
XS Rating Curve= 0 ,0
Exp/Cntr=0.3,0.1

Type RM Length L Ch R = 1 ,2269.1  ,267.7,262.9,258
XS GIS Cut Line= 2
     1891784.625      308870.398     1891704.329      309193.749
#Sta/Elev= 26
       0 1749.78    19.6 1742.61    58.8 1728.06    68.6 1724.49    78.4 1720.94
    88.2 1717.77      98  1716.3   107.8 1715.93   117.6 1715.76   127.4  1715.7
   166.6 1715.82   176.4 1715.41   186.2  1714.5     196 1713.36   205.8 1713.85
   215.6 1715.64   225.4 1717.19   235.2 1718.27     245 1719.22   254.8 1720.74
   264.6 1723.31   284.2 1729.82     294 1733.18   303.8 1736.68   313.6 1740.36
   333.2 1747.98
#Mann= 3 , 0 , 0
       0      .1       0   176.4    .045       0   215.6      .1       0
Bank Sta=176.4,215.6
XS Rating Curve= 0 ,0
Exp/Cntr=0.3,0.1

Type RM Length L Ch R = 1 ,2006.3  ,327.3,341.2,355.1
XS GIS Cut Line= 2
     1891484.744      308883.946     1891476.835      309146.904
#Sta/Elev= 30
       0 1713.81     9.7 1713.45    19.5 1713.09    29.2  1712.7      39 1712.29
    48.7 1711.87    58.5 1711.45    68.2 1711.01      78 1710.55    87.7  1710.1
    97.4 1709.64   107.2 1709.03   116.9 1708.14   122.5 1707.63   126.7 1707.24
   136.4 1707.37   137.5 1707.55   146.2 1709.01   155.9    1711   165.6 1712.56
   175.4 1713.93   185.1 1715.31   194.9 1716.86   204.6 1719.13   214.4 1722.72
   224.1 1727.41   233.8 1732.45   243.6 1737.29   253.3 1741.53   263.1  1745.1
#Mann= 3 , 0 , 0
       0      .1       0   122.5    .045       0   137.5      .1       0
Bank Sta=122.5,137.5
XS Rating Curve= 0 ,0
Exp/Cntr=0.3,0.1

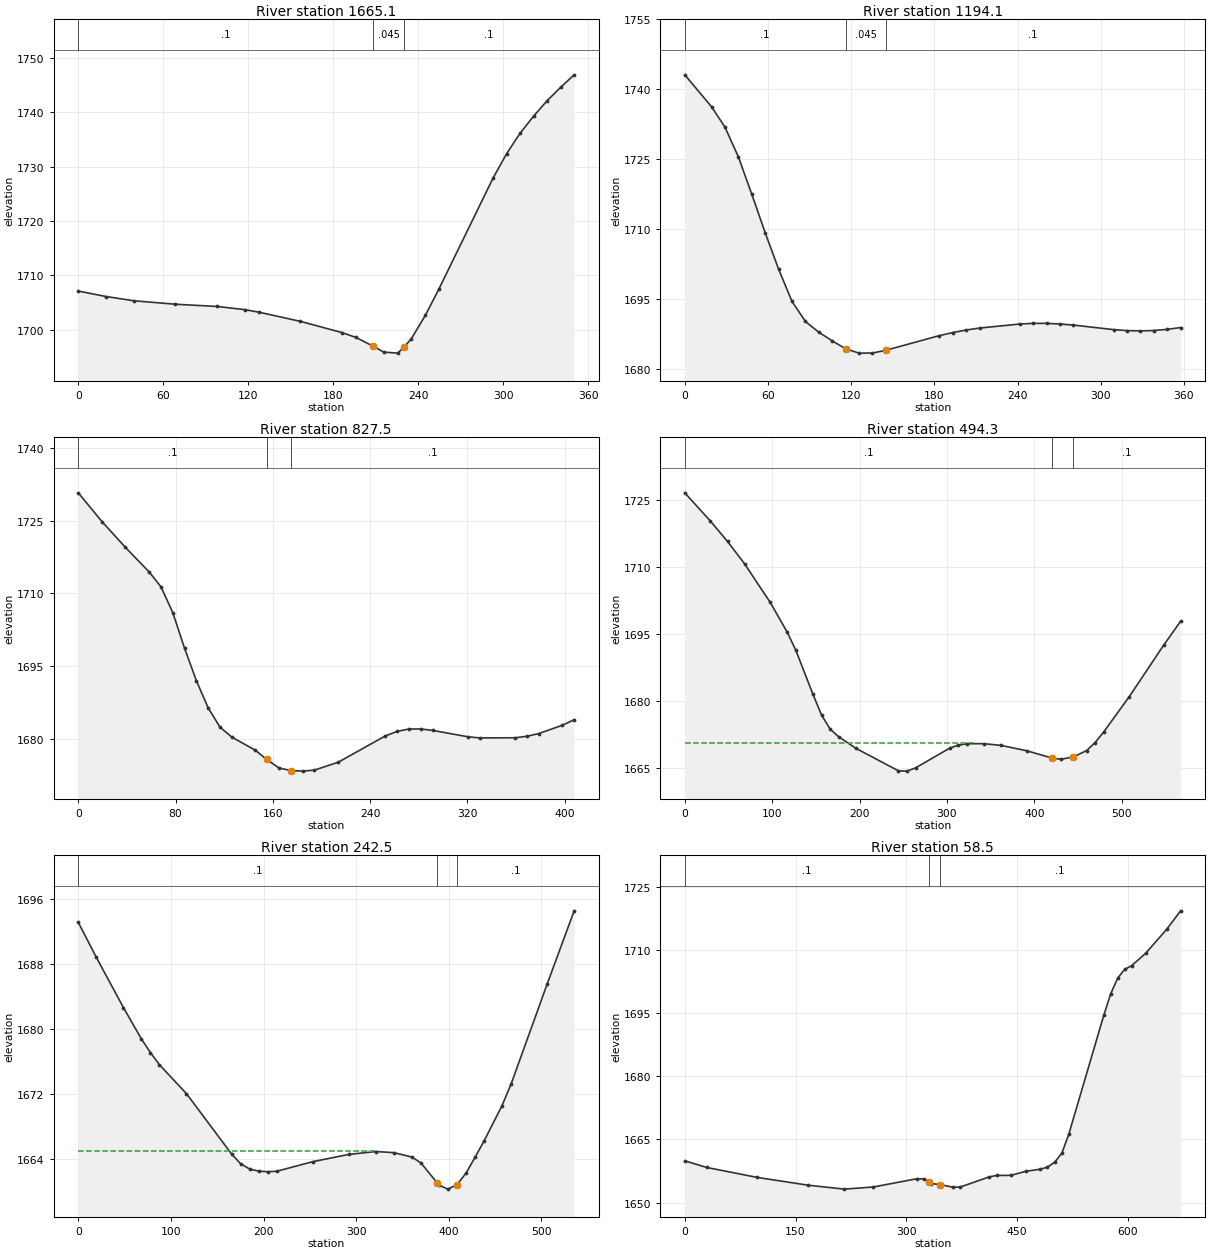
Type RM Length L Ch R = 1 ,1665.1  ,471.8,471.1,470.2
XS GIS Cut Line= 3
     1891287.663      308772.742     1891140.724      308968.962
     1891111.068      309069.796
#Sta/Elev= 24
       0 1707.09    19.6 1706.08    39.2  1705.3    68.6 1704.66    98.1 1704.25
   117.7 1703.66   127.5  1703.2   156.9  1701.5   186.3 1699.43   196.1 1698.54
   208.2 1696.93   215.7 1695.84   225.5 1695.65  229.86 1696.69   235.3 1698.34
   245.1 1702.61   254.7 1707.48   292.9  1727.9   302.5 1732.41     312 1736.17
   321.6 1739.34   331.1 1742.17   340.7 1744.65   350.2 1746.94
#Mann= 3 , 0 , 0
       0      .1       0   208.2    .045       0  229.86      .1       0
Bank Sta=208.2,229.86
XS Rating Curve= 0 ,0
Exp/Cntr=0.3,0.1

Type RM Length L Ch R = 1 ,1194.1  ,368.2,366.5,364.8
XS GIS Cut Line= 2
      1890992.44      308452.933     1890786.819      308745.547
#Sta/Elev= 30
       0 1743.06    19.3 1736.21      29 1731.82    38.7 1725.42    48.3 1717.45
      58 1709.16    67.7 1701.33    77.3 1694.45      87 1690.14    96.7 1687.82
   106.3 1685.99     116 1684.28   125.7 1683.35   135.3 1683.37     145 1683.96
   183.6 1687.11   193.3 1687.76     203 1688.31   212.6 1688.73   241.6 1689.59
   251.3 1689.74     261 1689.73   270.6  1689.6   280.3 1689.37   309.3 1688.39
     319 1688.18   328.6 1688.12   338.3  1688.2     348 1688.46   357.6 1688.84
#Mann= 3 , 0 , 0
       0      .1       0     116    .045       0     145      .1       0
Bank Sta=116,145
XS Rating Curve= 0 ,0
Exp/Cntr=0.3,0.1

Type RM Length L Ch R = 1 ,827.5   ,345,333.3,321.5
XS GIS Cut Line= 2
     1890695.872       308221.61     1890486.297      308571.561
#Sta/Elev= 30
       0 1730.71    19.4 1724.79    38.8 1719.45    58.3 1714.38      68 1711.33
    77.7 1706.01    87.4 1698.65    97.1 1691.97   106.8 1686.39   116.5  1682.4
   126.3 1680.33   145.7 1677.62   154.8 1675.74   165.1 1673.97   174.8 1673.44
   184.5 1673.32   194.2 1673.53   213.7 1675.14   252.5 1680.57   262.2 1681.51
   271.9    1682   281.6 1682.02   291.4 1681.72   320.5  1680.4   330.2 1680.17
   359.4  1680.2   369.1 1680.51   378.8 1681.07   398.2 1682.78   407.9 1683.93
#Mann= 3 , 0 , 0
       0      .1       0   154.8    .045       0   174.8      .1       0
Bank Sta=154.8,174.8
XS Rating Curve= 0 ,0
Exp/Cntr=0.3,0.1

Type RM Length L Ch R = 1 ,494.3   ,248,251.7,255.5
XS GIS Cut Line= 3
      1890389.39      307983.973      1890306.98      308150.522
     1890299.185       308532.14
#Sta/Elev= 30
       0 1726.59    29.3 1720.28    48.9 1715.73    68.5 1710.71    97.8  1702.1
   117.4 1695.39   127.1  1691.4   146.7 1681.56   156.5 1676.95   166.3  1673.8
     176 1672.11   195.6 1669.53   244.5 1664.48   254.3 1664.41   264.1 1665.13
   303.3 1669.56     313 1670.21   322.8 1670.53   342.4 1670.54     362 1670.16
   391.4 1668.96   420.7 1667.31   430.5 1667.06   444.8 1667.59   459.9    1669
   469.6 1670.79   479.4 1673.14   508.8 1681.07   547.9  1692.5   567.5  1697.9
#Mann= 3 , 0 , 0
       0      .1       0   420.7    .045       0   444.8      .1       0
#XS Ineff= 2 , 0
          332.11  1670.8
Permanent Ineff=
       F       F
Bank Sta=420.7,444.8
XS Rating Curve= 0 ,0
Exp/Cntr=0.3,0.1

Type RM Length L Ch R = 1 ,242.5   ,188.3,184,179.8
XS GIS Cut Line= 2
     1890132.391      307964.584     1890032.041      308490.507
#Sta/Elev= 30
       0 1693.17    19.5 1688.86    48.7 1682.69    68.1 1678.83    77.9 1677.14
    87.6 1675.65   116.8 1672.09   165.5 1664.66   175.2 1663.47     185 1662.81
   194.7 1662.56   204.4 1662.48   214.2 1662.54   253.1 1663.72     292 1664.61
   321.2 1664.97   340.7 1664.83   360.2 1664.29   369.9 1663.57   387.3 1661.14
   389.4 1660.83   399.1 1660.34   408.9 1660.89   418.6  1662.3   428.3 1664.24
   438.1 1666.26   457.5 1670.62   467.3 1673.27   506.2 1685.57   535.4  1694.6
#Mann= 3 , 0 , 0
       0      .1       0   387.3    .045       0   408.9      .1       0
#XS Ineff= 2 , 0
          321.13 1665.06
Permanent Ineff=
       F       F
Bank Sta=387.3,408.9
XS Rating Curve= 0 ,0
Exp/Cntr=0.3,0.1

Type RM Length L Ch R = 1 ,58.5    ,59.5,58.5,57.5
XS GIS Cut Line= 3
      1889878.83      307990.663      1889878.83      308501.242
     1889985.201      308621.795
#Sta/Elev= 30
       0 1659.91    29.5 1658.34    98.2 1655.96   166.9 1654.12     216 1653.18
   255.3 1653.69   314.2 1655.65     324 1655.61   330.2 1654.91   333.8  1654.5
   345.2 1654.27   363.3 1653.64   373.1 1653.68   412.4  1656.1   422.2 1656.43
   441.8 1656.46   461.5 1657.41   481.1 1657.91   490.9 1658.39   500.8 1659.57
   510.6 1661.72     520 1666.26   567.3 1694.48   576.8 1699.66   586.2 1703.36
   595.7 1705.44   605.2 1706.34   624.1 1709.26   652.4 1714.94   671.4 1719.36
#Mann= 3 , 0 , 0
       0      .1       0   330.2    .045       0   345.2      .1       0
Bank Sta=330.2,345.2
XS Rating Curve= 0 ,0
Exp/Cntr=0.3,0.1

Chan Stop Cuts=-1
Use User Specified Reach Order=0
Composite Channel Slope=5